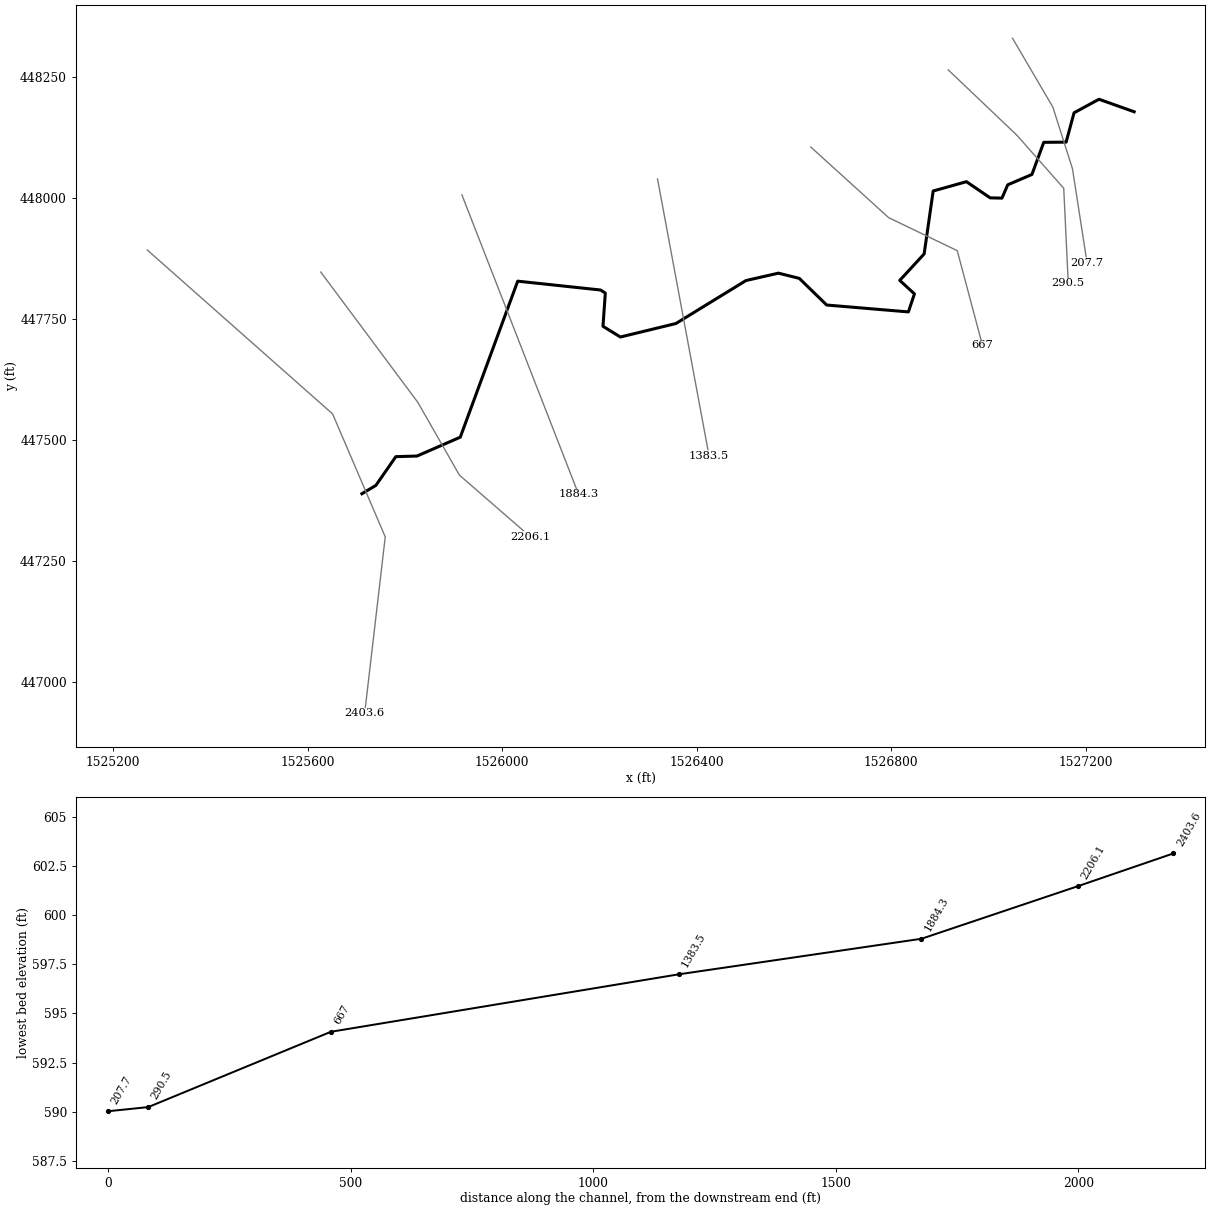
--- BLACKFK.prj (project) ---

Proj Title=BLACKFK
Current Plan=p01
Default Exp/Contr=0,0
English Units
Geom File=g01
Flow File=f01
Plan File=p01
BEGIN DESCRIPTION:
END DESCRIPTION:
DSS Export Rating Curves= 0
DSS Export Rating Curve Sorted= 0
DSS Export Volume Flow Curves= 0
DXF OffsetX= 0
DXF OffsetY= 0
DXF ScaleX= 0
DXF ScaleY= 0

--- BLACKFK.p01 (plan) ---

Plan Title=Floodplain
Program Version=4.00
Geom File=g01
Flow File=f01
K Sum by GR=0
Std Step Tol=0.01
Critical Tol=0.01
Num of Std Step Trials=20
Max Error Tol=0.3
Flow Tol Ratio=0.001
Split Flow NTrial=30
Split Flow Tol=0.02
Split Flow Ratio=0.02
Log Output Level=0
Friction Slope Method=1
Unsteady Friction Slope Method=2
Unsteady Bridges Friction Slope Method=1
Global Log Level=0
CheckData=False
Run HTab=0
Run UNet=0
Run PostProcess=0
UNET Theta=0
UNET Theta Warmup=0
UNET ZTol=0
UNET ZSATol=0
UNET MxIter=0
UNET MaxInSteps=0
UNET DtIC=0
UNET DtMin=0
UNET MaxCRTS=0
UNET WFStab=0
UNET SFStab=0
UNET WFX=0
UNET SFX=0
UNET DSS MLevel=0
UNET DZMax Abort=0
UNET Convert EG Bridges=0
UNET Use Existing IB Tables=0
UNET Froude Limit=0
UNET Froude Power=0
Write IC File=0
Echo Input=False
Echo Output=False
Write Detailed=0

--- BLACKFK.f01 (steady flow) ---

Flow Title=NFF Regression Equation
Program Version=4.00
Number of Profiles= 1
Profile Names=P100yr
River Rch & RM=BLACKFK,Main            ,2403.6
471.6907
River Rch & RM=BLACKFK,Main            ,290.5
498.1372
Boundary for River Rch & Prof#=BLACKFK,Main            , 1
Up Type= 0
Dn Type= 3
Dn Slope=0.006
DSS Import GetInterval= 0
DSS Import GetPeak= 0
DSS Import FillOption= 0

--- BLACKFK.g01 (geometry) ---

Geom Title=Geometry
Program Version=4.00

River Reach=BLACKFK         ,Main
Reach XY= 30
      1525711.73      447389.378     1525740.484      447406.667
     1525781.449      447466.001     1525825.013      447467.291
     1525913.998      447506.229     1526032.113      447828.643
     1526202.509      447810.365     1526212.279      447804.036
     1526207.478      447735.431     1526243.233      447713.224
     1526357.465       447741.12     1526501.559      447829.941
     1526568.329      447845.195      1526611.21       447834.41
     1526667.565       447779.32     1526835.572      447765.115
     1526847.991      447802.396      1526817.82      447830.248
     1526867.952      447884.914     1526886.534      448014.955
     1526954.959      448034.212     1527003.727      448000.801
     1527027.944      448000.216     1527039.864      448027.737
     1527089.636      448049.134     1527113.905      448115.525
     1527159.909      448115.922     1527176.279      448176.582
     1527227.557      448204.549     1527299.858      448178.685

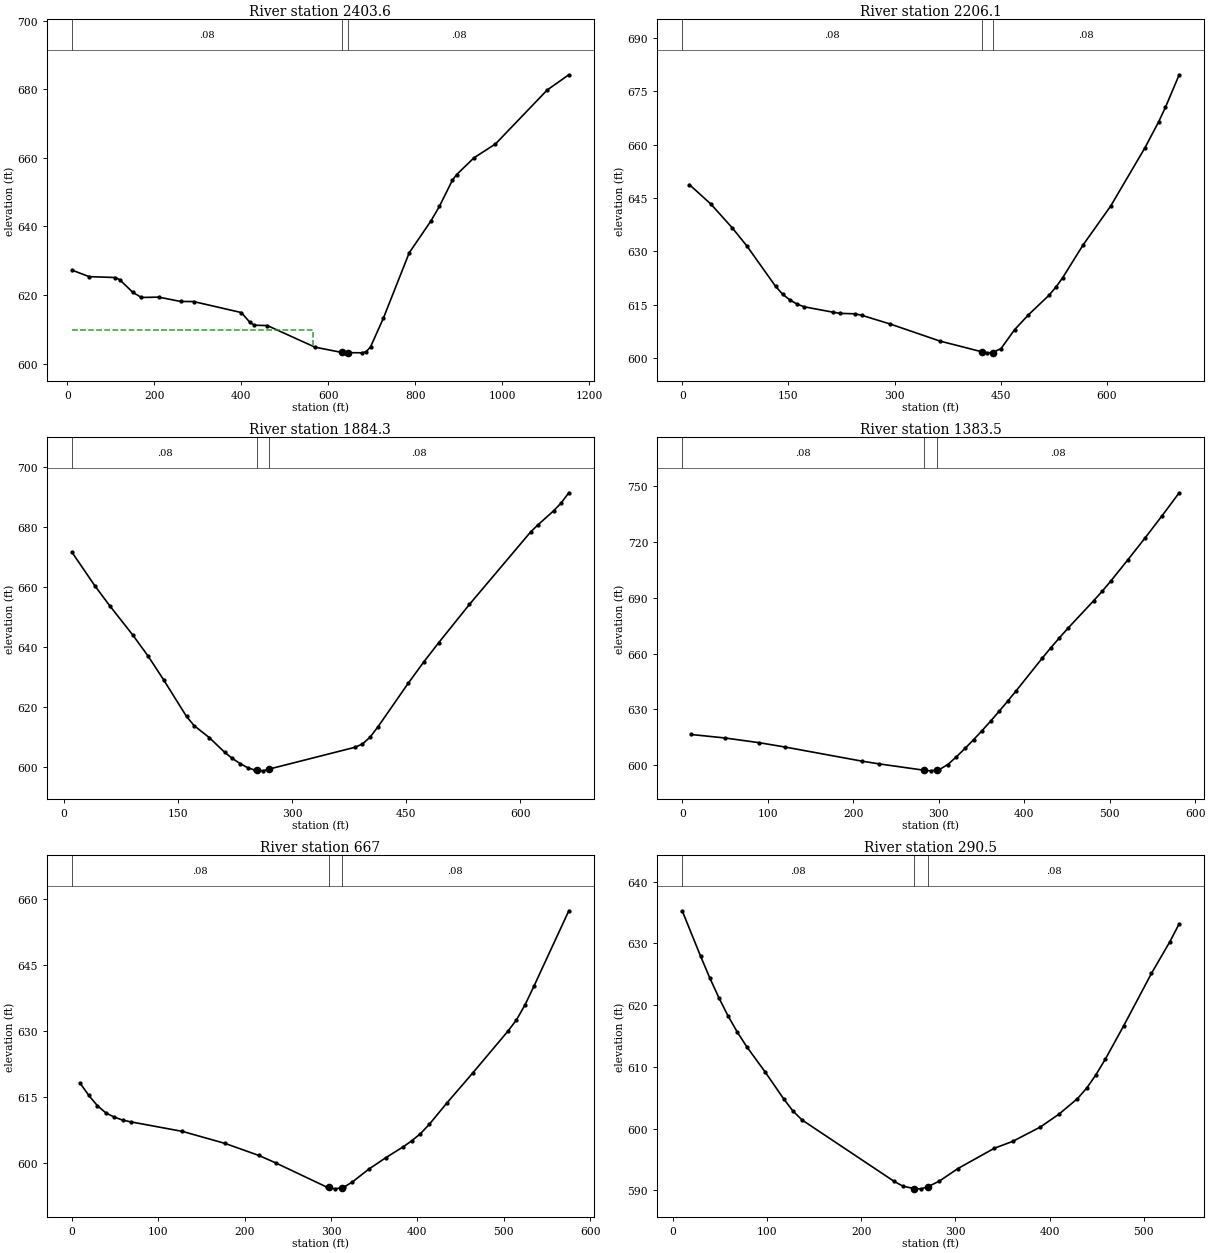
Type RM Length L Ch R = 1 ,2403.6  ,195,197.4,199.8
XS GIS Cut Line= 4
     1525270.361      447893.031     1525651.484      447554.256
     1525759.704      447300.174     1525717.357       446935.52
#Sta/Elev= 30
      10  627.28      50  625.37     110  625.11     120  624.49     150  620.82
     170  619.29     210  619.39     260  618.13     290   618.1   399.9  614.89
   419.9     612   429.9   611.2   459.9  611.09   569.1  604.81   630.6  603.26
   638.1  603.14   645.6  603.19   677.6  603.15   687.5  603.49   697.3  604.93
   726.9  613.32   786.1  632.33   835.7  641.54   855.5  645.86   885.3  653.47
   895.2  655.14   934.9  660.01   984.5  664.07  1103.6  679.82  1153.2  684.25
#Mann= 3 , 0 , 0
      10     .08       0   630.6    .045       0   645.6     .08       0
#XS Ineff= 2 , 0
          563.81  609.87
Permanent Ineff=
       F       F
Bank Sta=630.6,645.6
XS Rating Curve= 0 ,0
Exp/Cntr=0.3,0.1

Type RM Length L Ch R = 1 ,2206.1  ,330.2,321.9,317.4
XS GIS Cut Line= 4
     1525627.141      447847.432     1525826.523      447578.499
     1525912.303      447427.804     1526058.361      447300.293
#Sta/Elev= 30
    10.1  648.76    40.6  643.27      71  636.53    91.3  631.53   131.9  620.17
     142  617.92   152.2  616.33   162.3  615.16   172.5   614.4     213   612.9
   223.2  612.56   243.5  612.45   253.6  612.03   294.2  609.55   363.7   604.8
   423.6  601.75   431.1  601.47   438.6  601.56   450.4  602.67   469.6  607.98
   488.9   612.1   517.9   617.6   527.6  619.85   537.3  622.53   566.3  631.79
   605.1  642.66   653.6  659.06     673  666.37   682.7  670.49   702.1  679.63
#Mann= 3 , 0 , 0
       0     .08       0   423.6    .045       0   438.6     .08       0
Bank Sta=423.6,438.6
XS Rating Curve= 0 ,0
Exp/Cntr=0.3,0.1

Type RM Length L Ch R = 1 ,1884.3  ,502.5,500.7,493.8
XS GIS Cut Line= 2
     1525917.371      448006.949     1526157.337      447388.213
#Sta/Elev= 30
    10.1  671.74    40.2  660.56    60.3  653.72    90.5     644   110.6  636.97
   130.7  629.19   160.9  616.93   170.9  613.87     191  609.85   211.2  604.94
   221.2  602.94   231.3  601.23   241.3  599.84   251.4  599.01   253.9  599.01
   261.4   598.8   268.9  599.35   382.1  606.63   392.2  607.73   402.2  610.01
   412.3  613.35   452.5  628.02   472.6  635.01   492.7  641.58   532.9  654.27
   613.4  678.44   623.4   680.9   643.5  685.45   653.6  688.13   663.6   691.5
#Mann= 3 , 0 , 0
    10.1     .08       0   253.9    .045       0   268.9     .08       0
Bank Sta=253.9,268.9
XS Rating Curve= 0 ,0
Exp/Cntr=0.3,0.1

Type RM Length L Ch R = 1 ,1383.5  ,695.9,716.5,727.1
XS GIS Cut Line= 2
     1526319.667      448039.885     1526425.534      447468.202
#Sta/Elev= 30
      10  616.55    50.1  614.65    90.2  612.11   120.3  609.79   210.5  602.18
   230.6  600.71   283.2   597.3   290.7  596.99   298.2  597.49   300.7  597.65
   310.8  600.39   320.8  604.55   330.8  609.03   340.8  613.68   350.8   618.6
   360.9  623.75   370.9  629.06   380.9  634.51   390.9  640.14     421  657.44
     431  663.02   441.1  668.39   451.1  673.54   481.2  688.35   491.2  693.44
   501.2  698.89   521.3  710.39   541.3  722.06   561.4   734.1   581.4  746.45
#Mann= 3 , 0 , 0
       0     .08       0   283.2    .045       0   298.2     .08       0
Bank Sta=283.2,298.2
XS Rating Curve= 0 ,0
Exp/Cntr=0.3,0.1

Type RM Length L Ch R = 1 ,667     ,389.3,376.5,363.9
XS GIS Cut Line= 4
     1526634.916      448105.758     1526794.893      447959.897
      1526936.05      447891.671     1526987.807      447696.405
#Sta/Elev= 30
     9.8  618.07    19.7  615.33    29.5  613.03    39.4  611.36    49.2  610.41
      59  609.71    68.9   609.3   127.9  607.16   177.1  604.43   216.5  601.67
   236.1  599.97   294.9  594.49   297.2  594.39   304.7  594.07   312.2  594.32
   314.5   594.4   324.3  595.57   343.9  598.57   363.5  601.17   383.4  603.62
   393.5  605.01   403.6  606.64   413.7  608.74   433.9  613.56   464.2  620.48
   504.6  629.93   514.7  632.55   524.8  636.04   534.9  640.21   575.3   657.4
#Mann= 3 , 0 , 0
       0     .08       0   297.2    .045       0   312.2     .08       0
Bank Sta=297.2,312.2
XS Rating Curve= 0 ,0
Exp/Cntr=0.3,0.1

Type RM Length L Ch R = 1 ,290.5   ,96.6,82.8,70.4
XS GIS Cut Line= 4
     1526917.603      448265.152     1527059.028       448129.92
     1527155.033      448020.496     1527164.324      447824.358
#Sta/Elev= 30
     9.8   635.3    29.4  627.91    39.1  624.42    48.9  621.16    58.7   618.2
    68.5   615.6    78.3  613.28    97.8   609.2   117.4  604.86   127.2  602.89
     137  601.41   234.5  591.49   244.2  590.67   256.1  590.28   263.6  590.24
   271.1  590.61     283   591.5   302.4  593.51   341.2  596.81   360.9  597.94
   390.3  600.27     410  602.35   429.6  604.86   439.4  606.56   449.2  608.73
   459.1  611.24   478.7  616.67   508.1  625.14   527.8  630.31   537.6   633.2
#Mann= 3 , 0 , 0
     9.8     .08       0   256.1    .045       0   271.1     .08       0
Bank Sta=256.1,271.1
XS Rating Curve= 0 ,0
Exp/Cntr=0.3,0.1

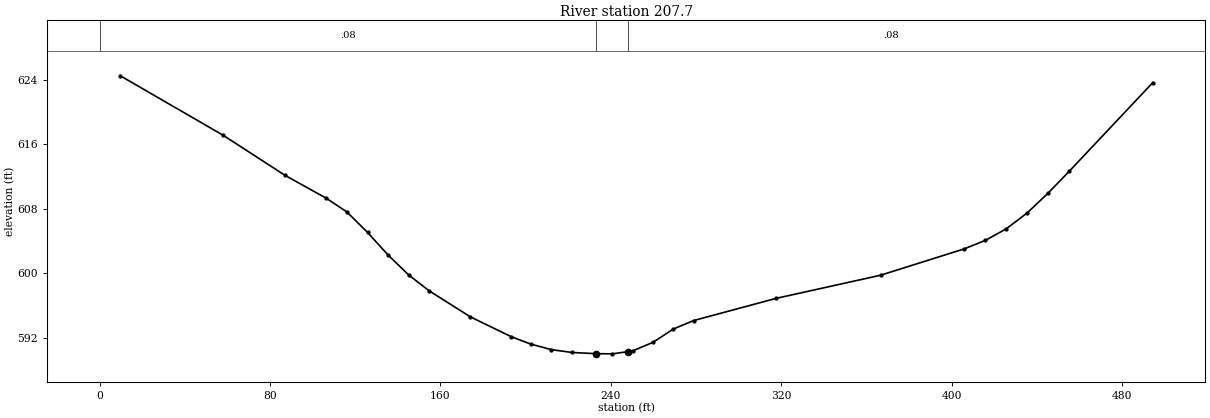
Type RM Length L Ch R = 1 ,207.7   ,202.2,207.7,203.6
XS GIS Cut Line= 4
     1527049.775      448330.428     1527132.672      448188.319
     1527172.936      448061.211     1527202.937      447866.995
#Sta/Elev= 30
     9.7  624.49    58.1   617.1    87.1  612.14   106.5   609.3   116.1  607.61
   125.8  605.07   135.5  602.25   145.2  599.78   154.8  597.82     174  594.62
   193.1  592.17   202.6  591.22   212.1  590.55   221.7   590.2   233.2  590.05
   240.7  590.03   248.2  590.31   250.2  590.39   259.8  591.46   269.3   593.1
   278.8  594.15   317.5   596.9   366.6  599.77   405.9  603.04   415.8  604.09
   425.6  605.52   435.4  607.48   445.2  609.93   455.1  612.63   494.4  623.64
#Mann= 3 , 0 , 0
       0     .08       0   233.2    .045       0   248.2     .08       0
Bank Sta=233.2,248.2
XS Rating Curve= 0 ,0
Exp/Cntr=0.3,0.1

Chan Stop Cuts=-1
Use User Specified Reach Order=0